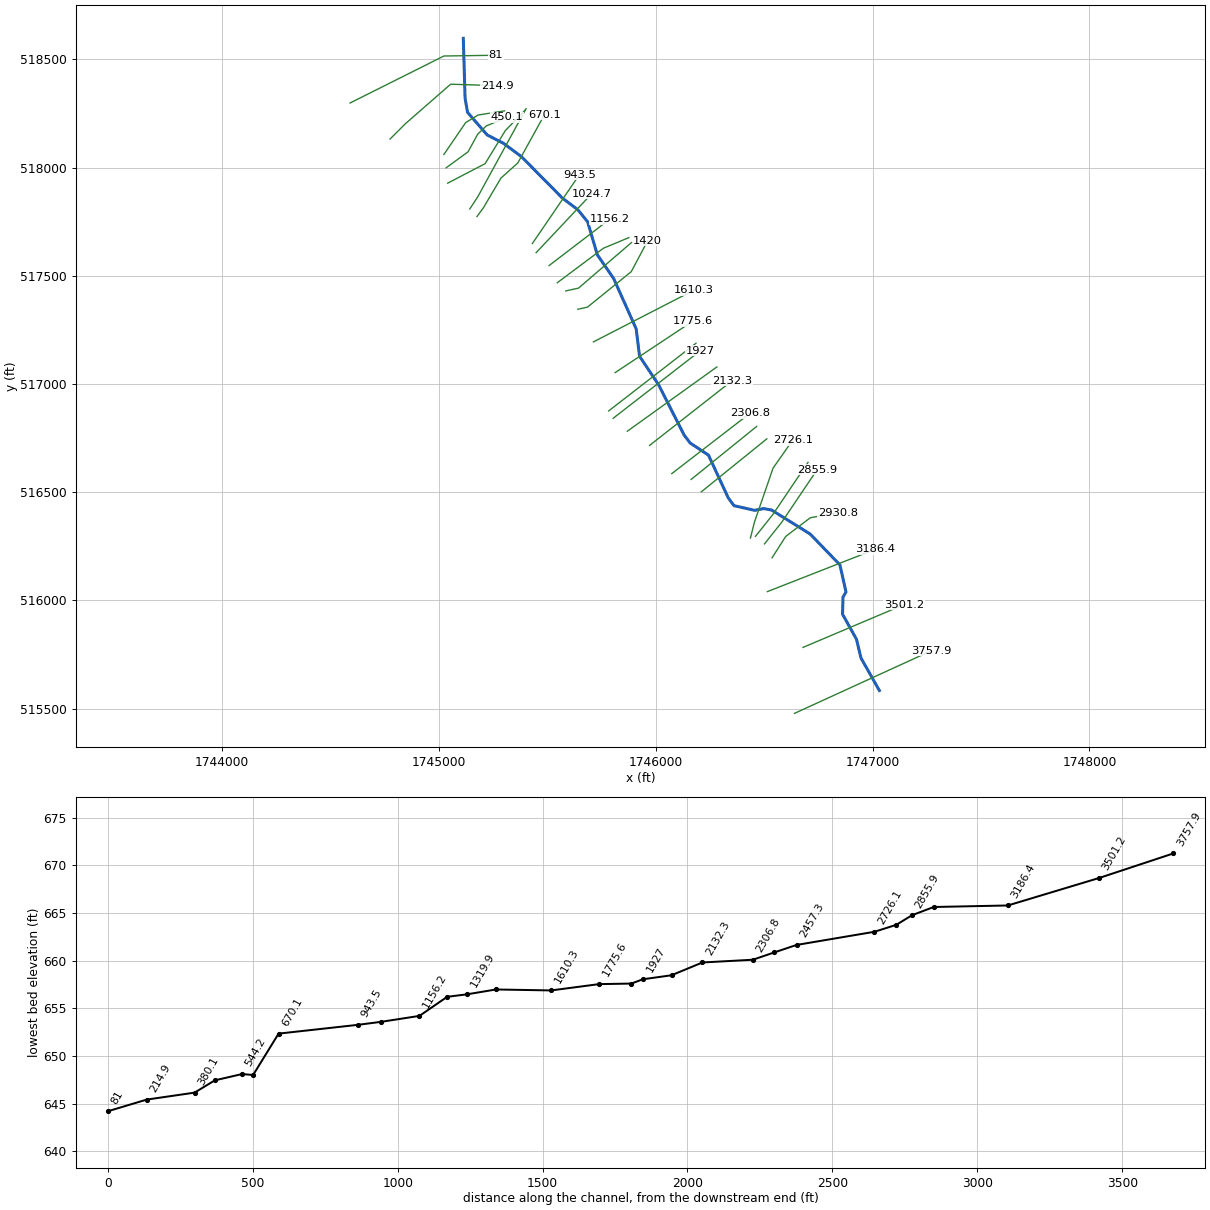
--- HOWARDFK.prj (project) ---

Proj Title=HOWARDFK
Current Plan=p01
Default Exp/Contr=0,0
English Units
Geom File=g01
Flow File=f01
Plan File=p01
BEGIN DESCRIPTION:
END DESCRIPTION:
DSS Export Rating Curves= 0
DSS Export Rating Curve Sorted= 0
DSS Export Volume Flow Curves= 0
DXF OffsetX= 0
DXF OffsetY= 0
DXF ScaleX= 0
DXF ScaleY= 0

--- HOWARDFK.p01 (plan) ---

Plan Title=Floodplain
Program Version=4.00
Geom File=g01
Flow File=f01
K Sum by GR=0
Std Step Tol=0.01
Critical Tol=0.01
Num of Std Step Trials=20
Max Error Tol=0.3
Flow Tol Ratio=0.001
Split Flow NTrial=30
Split Flow Tol=0.02
Split Flow Ratio=0.02
Log Output Level=0
Friction Slope Method=1
Unsteady Friction Slope Method=2
Unsteady Bridges Friction Slope Method=1
Global Log Level=0
CheckData=False
Run HTab=0
Run UNet=0
Run PostProcess=0
UNET Theta=0
UNET Theta Warmup=0
UNET ZTol=0
UNET ZSATol=0
UNET MxIter=0
UNET MaxInSteps=0
UNET DtIC=0
UNET DtMin=0
UNET MaxCRTS=0
UNET WFStab=0
UNET SFStab=0
UNET WFX=0
UNET SFX=0
UNET DSS MLevel=0
UNET DZMax Abort=0
UNET Convert EG Bridges=0
UNET Use Existing IB Tables=0
UNET Froude Limit=0
UNET Froude Power=0
Write IC File=0
Echo Input=False
Echo Output=False
Write Detailed=0

--- HOWARDFK.f01 (steady flow) ---

Flow Title=NFF Regression Equation
Program Version=4.10
Number of Profiles= 1
Profile Names=P100yr
River Rch & RM=HOWARDFK,Main            ,3757.9
879.2402
River Rch & RM=HOWARDFK,Main            ,3501.2
931.6339
River Rch & RM=HOWARDFK,Main            ,450.1
1026.287
Boundary for River Rch & Prof#=HOWARDFK,Main            , 1
Up Type= 0
Dn Type= 3
Dn Slope=0.006
DSS Import GetInterval= 0
DSS Import GetPeak= 0
DSS Import FillOption= 0

--- HOWARDFK.g01 (geometry) ---

Geom Title=USGS 10m DEM
Program Version=4.10

River Reach=HOWARDFK        ,Main
Reach XY= 30
     1747031.528      515584.069      1746946.79      515734.077
     1746925.957      515820.882     1746861.781      515936.496
     1746863.745      516016.098     1746877.635      516038.996
     1746849.568      516164.632     1746712.415      516306.993
     1746534.833       516417.79     1746498.028      516424.734
     1746457.055      516416.401     1746361.222      516437.929
     1746334.833       516474.04     1746243.665      516671.577
     1746159.139      516727.512     1746131.361      516764.318
     1746014.551      516995.099     1745925.957      517128.174
     1745910.332       517254.91     1745806.888      517486.727
     1745731.361      517596.957     1745686.374      517749.701
     1745641.235      517805.257     1745570.054      517859.077
     1745380.667      518051.123     1745298.028      518112.234
     1745223.722      518150.429     1745133.131      518254.913
     1745121.639      518319.873     1745113.457      518596.924

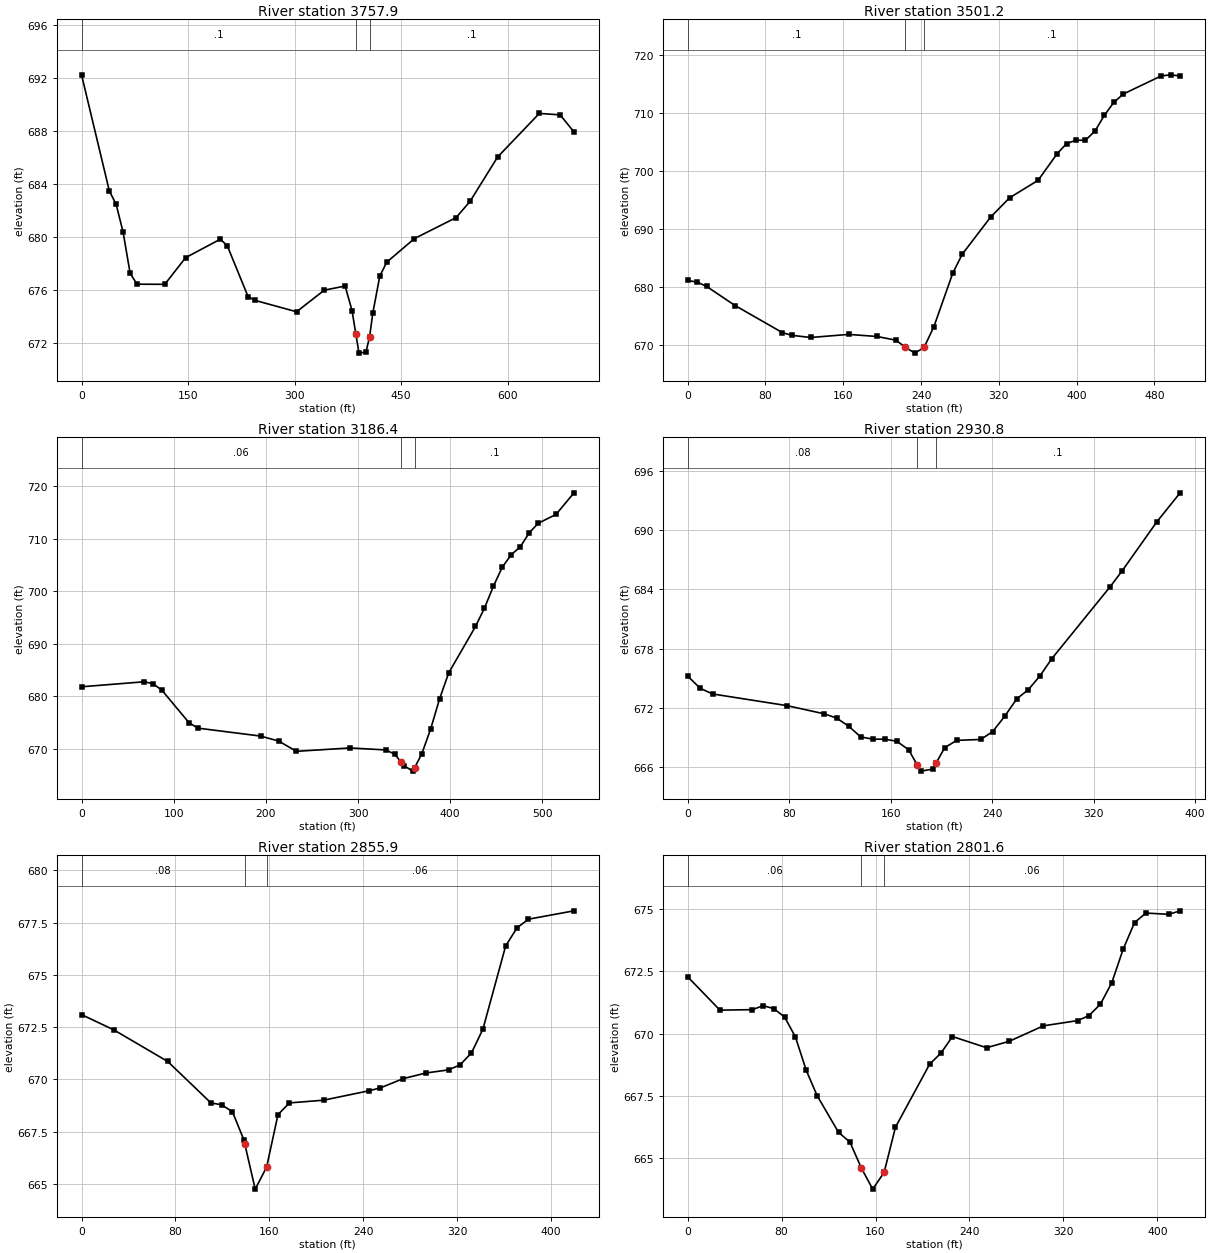
Type RM Length L Ch R = 1 ,3757.9  ,257.7,256.7,255.7
XS GIS Cut Line= 2
     1746640.273      515478.487     1747270.481      515767.549
#Sta/Elev= 30
       0  692.23    39.1  683.48    48.8  682.45    58.6  680.34    68.4  677.26
    78.1  676.44   117.2  676.43   146.5  678.44   195.3  679.83   205.1  679.35
   234.4  675.51   244.1  675.22   302.7  674.36   341.8  675.99   371.1   676.3
   380.8  674.45   386.1  672.71   390.6  671.24   400.4  671.32  405.49  672.46
   410.1  674.27   419.9  677.05   429.7   678.1   468.7  679.88   527.3  681.46
   546.9  682.68   585.9  686.04   644.5  689.32   673.8  689.21   693.3  687.92
#Mann= 3 , 0 , 0
       0      .1       0   386.1    .045       0  405.49      .1       0
Bank Sta=386.1,405.49
XS Rating Curve= 0 ,0
Exp/Cntr=0.3,0.1

Type RM Length L Ch R = 1 ,3501.2  ,315,314.8,314.5
XS GIS Cut Line= 2
     1746679.336      515783.174     1747145.481      515981.091
#Sta/Elev= 30
       0  681.15     9.7  680.88    19.5  680.13    48.7  676.85    97.4  672.19
   107.1  671.72   126.6  671.35   165.6  671.88   194.8  671.52   214.3  670.88
     224  669.64   233.7  668.66   243.1  669.64   253.2  673.21   272.7  682.46
   282.4  685.68   311.6  692.07   331.1  695.38   360.3  698.37   379.8  702.92
   389.6  704.69   399.3  705.28     409  705.26   418.8  706.84   428.5  709.55
   438.2  711.78     448  713.22   486.9  716.33   496.7  716.52   506.4  716.32
#Mann= 3 , 0 , 0
       0      .1       0     224    .045       0   243.1      .1       0
Bank Sta=224,243.1
XS Rating Curve= 0 ,0
Exp/Cntr=0.3,0.1

Type RM Length L Ch R = 1 ,3186.4  ,249.1,255.6,261.3
XS GIS Cut Line= 2
     1746515.273      516040.987     1747012.669      516236.299
#Sta/Elev= 30
       0  681.83      68  682.78    77.7   682.4    87.4  681.14   116.6     675
   126.3  673.96   194.3  672.45   213.8  671.51   233.2  669.55   291.5  670.19
   330.3  669.81     340  668.98   346.5  667.55   349.8  666.83   359.5  665.78
   361.5  666.45   369.2  669.05   378.9  673.82   388.6  679.57   398.4  684.45
   427.5   693.3   437.2  696.77   446.9  700.94   456.6  704.59   466.4  706.97
   476.1  708.45   485.8   711.1   495.5  712.93   514.9  714.62   534.4  718.73
#Mann= 3 , 0 , 0
       0     .06       0   346.5    .045       0   361.5      .1       0
Bank Sta=346.5,361.5
XS Rating Curve= 0 ,0
Exp/Cntr=0.3,0.1

Type RM Length L Ch R = 1 ,2930.8  ,67.6,74.9,83
XS GIS Cut Line= 4
     1746536.708      516197.188     1746600.076      516296.146
     1746712.924      516382.083      1746839.66      516405.521
#Sta/Elev= 29
       0  675.23     9.8     674    19.6  673.42    78.3  672.24   107.7  671.41
   117.5  670.98     127  670.15   136.4  669.08   145.9  668.85   155.3  668.85
   164.8  668.64   174.2  667.78   180.8  666.28   183.7  665.62   193.2  665.82
   195.8  666.42   202.6  667.99   212.1  668.73     231  668.82   240.4  669.61
   249.9  671.16   259.4  672.92   268.6  673.86   277.8  675.26     287  676.98
     333  684.25   342.2  685.81   369.8  690.81   388.2  693.75
#Mann= 3 , 0 , 0
       0     .08       0   180.8    .045       0   195.8      .1       0
Bank Sta=180.8,195.8
XS Rating Curve= 0 ,0
Exp/Cntr=0.3,0.1

Type RM Length L Ch R = 1 ,2855.9  ,54.7,54.3,54.4
XS GIS Cut Line= 3
     1746501.986      516261.424     1746581.847      516362.118
     1746744.174      516603.438
#Sta/Elev= 25
       0   673.1    27.5  672.37    73.4  670.86   110.2  668.88   119.3  668.79
   128.5  668.46   138.2  667.12   139.1   666.9   147.9  664.76   157.6  665.81
   167.3  668.32     177  668.88   206.1  669.01   244.8  669.46   254.6   669.6
   273.9  670.04   293.3  670.31   312.7  670.46   322.4   670.7   332.1  671.27
   341.8   672.4   361.2  676.38   370.9  677.25   380.6  677.66   419.4  678.06
#Mann= 3 , 0 , 0
       0     .08       0   139.1    .045       0   157.6     .06       0
Bank Sta=139.1,157.6
XS Rating Curve= 0 ,0
Exp/Cntr=0.3,0.1

Type RM Length L Ch R = 1 ,2801.6  ,71,75.5,80.7
XS GIS Cut Line= 3
     1746460.319      516296.146      1746540.18       516396.84
     1746702.507       516638.16
#Sta/Elev= 30
       0  672.28    27.5  670.94    55.1  670.96    64.3  671.12    73.4     671
    82.6  670.66    91.8  669.86     101  668.52   110.2  667.51   128.5  666.03
   138.2  665.64   147.9   664.6   157.6  663.75   167.3  664.42     177  666.24
   206.1  668.77   215.8  669.22   225.5  669.88   254.6  669.43   273.9  669.69
     303  670.31   332.1  670.52   341.8  670.72   351.5  671.18   361.2  672.04
   370.9  673.39   380.6  674.46   390.3  674.84   409.7  674.79   419.4  674.93
#Mann= 3 , 0 , 0
       0     .06       0   147.9    .045       0   167.3     .06       0
Bank Sta=147.9,167.3
XS Rating Curve= 0 ,0
Exp/Cntr=0.3,0.1

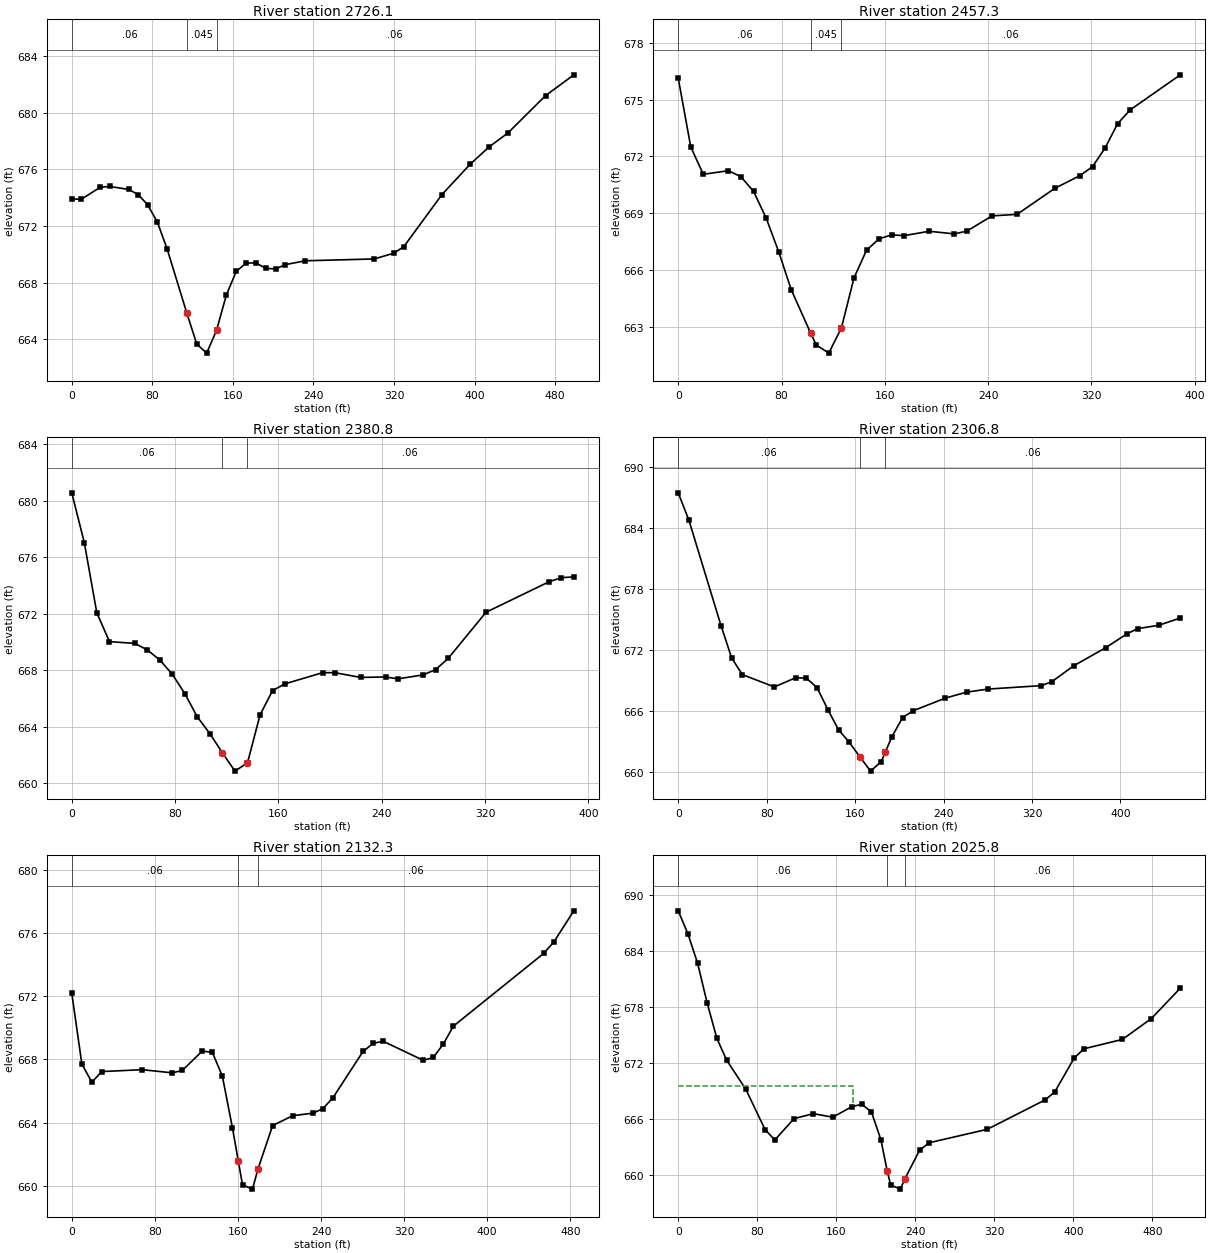
Type RM Length L Ch R = 1 ,2726.1  ,279.8,268.7,256.1
XS GIS Cut Line= 4
     1746437.148      516288.383     1746455.377      516361.299
     1746541.315      516611.299     1746632.461      516741.508
#Sta/Elev= 30
       0  673.91     9.4  673.88    28.2  674.73    37.6  674.79    56.4  674.58
    65.8  674.22    75.2  673.51      85  672.27    94.7  670.37   114.3  665.83
   124.1  663.66   133.9  663.02   143.7  664.62   153.5  667.13   163.3  668.79
   173.1  669.38   182.9  669.39   192.6     669   202.4  668.97   212.2  669.27
   231.8  669.54   300.4  669.67   319.9  670.08   329.7  670.54   367.6  674.22
   395.6  676.36   414.3  677.58     433  678.56   470.4   681.2   498.5  682.67
#Mann= 3 , 0 , 0
       0     .06       0   114.3    .045       0   143.7     .06       0
Bank Sta=114.3,143.7
XS Rating Curve= 0 ,0
Exp/Cntr=0.3,0.1

Type RM Length L Ch R = 1 ,2457.3  ,76.6,76.5,76.5
XS GIS Cut Line= 2
     1746210.586      516501.924     1746512.669      516746.716
#Sta/Elev= 30
       0  676.12     9.7   672.5    19.4  671.06    38.9  671.25    48.6  670.93
    58.3  670.16      68  668.77    77.8  666.98    87.5  664.98   102.5   662.7
   106.9  662.07   116.6  661.64   126.4  662.98   136.1   665.6   145.8  667.06
   155.5  667.66   165.2  667.87     175  667.83   194.4  668.06   213.8  667.92
   223.6  668.07     243  668.87   262.4  668.95   291.6  670.32     311  670.99
   320.8  671.46   330.5  672.44   340.2  673.72   349.9  674.45   388.8   676.3
#Mann= 3 , 0 , 0
       0     .06       0   102.5    .045       0   126.4     .06       0
Bank Sta=102.5,126.4
XS Rating Curve= 0 ,0
Exp/Cntr=0.3,0.1

Type RM Length L Ch R = 1 ,2380.8  ,74.9,74.1,72.9
XS GIS Cut Line= 2
     1746163.711      516559.216     1746465.794      516804.008
#Sta/Elev= 30
       0  680.55     9.7  677.03    19.4  672.06    29.2  670.02    48.6   669.9
    58.3  669.45      68  668.74    77.8  667.72    87.5  666.35    97.2   664.7
   106.9  663.52   116.6  662.16   126.4  660.86   135.4  661.41   136.1  661.45
   145.8  664.84   155.5  666.56   165.2  667.04   194.4  667.83   204.1  667.82
   223.6  667.49     243  667.52   252.7  667.39   272.2  667.67   281.9  668.05
   291.6  668.85   320.8   672.1   369.4  674.25   379.1  674.55   388.8   674.6
#Mann= 3 , 0 , 0
       0     .06       0   116.6    .045       0   135.4     .06       0
Bank Sta=116.6,135.4
XS Rating Curve= 0 ,0
Exp/Cntr=0.3,0.1

Type RM Length L Ch R = 1 ,2306.8  ,173.9,174.4,175
XS GIS Cut Line= 2
     1746074.474      516586.053     1746433.849      516863.831
#Sta/Elev= 30
       0  687.46     9.7  684.75    38.7   674.4    48.3  671.23      58  669.58
      87  668.37   106.3  669.28     116  669.23   125.6   668.3   135.3  666.15
     145  664.16   154.6  662.94   164.3   661.5     174  660.09   183.6  661.03
   187.3  661.96   193.3  663.47     203  665.36   212.6  666.03   241.6  667.27
   260.9  667.86   280.3  668.16   328.6   668.5   338.2   668.9   357.6  670.44
   386.6  672.22   405.9  673.59   415.6   674.1   434.9  674.44   454.2  675.15
#Mann= 3 , 0 , 0
       0     .06       0   164.3    .045       0   187.3     .06       0
Bank Sta=164.3,187.3
XS Rating Curve= 0 ,0
Exp/Cntr=0.3,0.1

Type RM Length L Ch R = 1 ,2132.3  ,107.3,106.5,105.5
XS GIS Cut Line= 2
     1745972.044      516716.262     1746352.252      517014.873
#Sta/Elev= 30
       0  672.19     9.7  667.71    19.3  666.56      29  667.23    67.7  667.35
    96.7  667.15   106.4   667.3   125.7  668.53   135.4  668.44     145  666.94
   154.7  663.67   160.4  661.55   164.4  660.07     174   659.8  179.36  661.09
   193.4  663.82   212.7  664.44   232.1   664.6   241.7  664.88   251.4  665.57
   280.4   668.5   290.1  669.01   299.7  669.15   338.4  667.94   348.1  668.12
   357.8  668.98   367.4   670.1   454.4   674.7   464.1  675.42   483.4  677.39
#Mann= 3 , 0 , 0
       0     .06       0   160.4    .045       0  179.36     .06       0
Bank Sta=160.4,179.36
XS Rating Curve= 0 ,0
Exp/Cntr=0.3,0.1

Type RM Length L Ch R = 1 ,2025.8  ,98,98.8,99.6
XS GIS Cut Line= 2
      1745869.44      516781.872       1746282.2      517078.747
#Sta/Elev= 30
       0  688.33     9.8  685.86    19.6  682.71    29.3  678.43    39.1  674.65
    48.9  672.32    68.4  669.18      88  664.84    97.8  663.74   117.3  666.03
   136.9  666.56   156.4  666.18     176  667.32   185.8  667.56   195.6  666.76
   205.3  663.73  211.51  660.45   215.1  658.91   224.9  658.46   229.3  659.52
   244.4  662.64   254.2  663.44   312.9  664.88   371.6  668.04   381.3   668.9
   400.9  672.52   410.7  673.52   449.8  674.53   479.1  676.77   508.4  680.03
#Mann= 3 , 0 , 0
       0     .06       0  211.51    .045       0   229.3     .06       0
#XS Ineff= 2 , 0
          176.97  669.51
Permanent Ineff=
       F       F
Bank Sta=211.51,229.3
XS Rating Curve= 0 ,0
Exp/Cntr=0.3,0.1

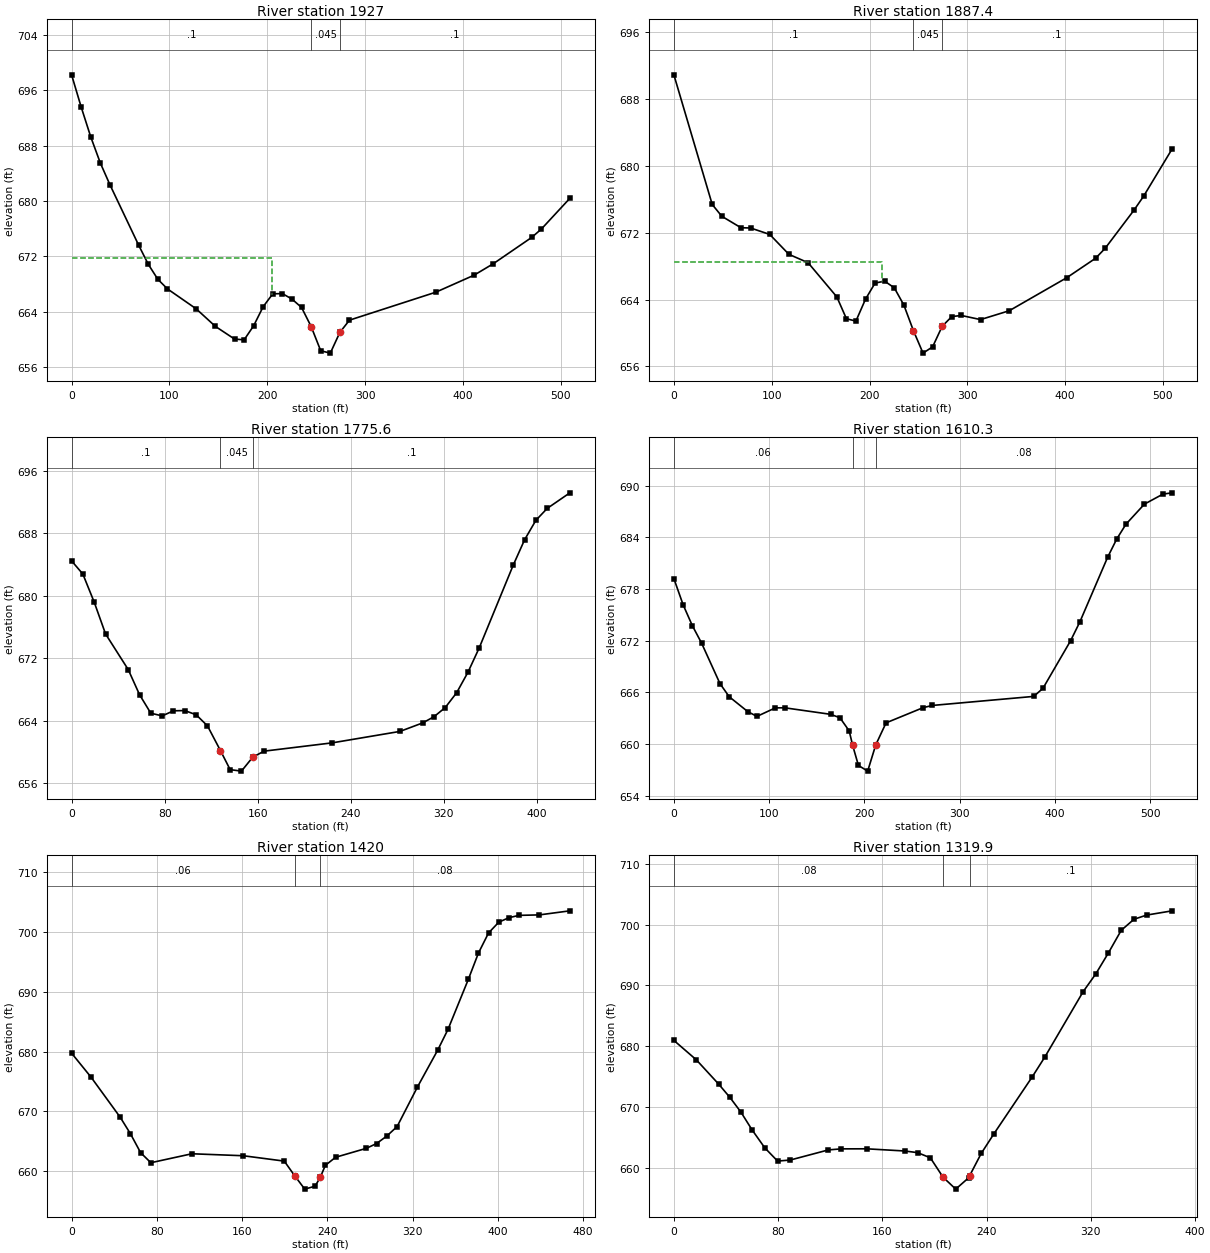
Type RM Length L Ch R = 1 ,1927    ,39.6,39.6,39.6
XS GIS Cut Line= 2
     1745804.336      516841.768     1746206.679      517154.268
#Sta/Elev= 30
       0   698.2     9.8  693.56    19.6  689.24    29.4  685.47    39.2  682.34
    68.6  673.61    78.4  670.86    88.2  668.69      98  667.31   127.4  664.43
     147   661.9   166.6  660.07   176.4  659.96   186.1  661.98   195.9  664.75
   205.7   666.6   215.5  666.63   225.3  665.84   235.1  664.63   244.9  661.88
   254.7  658.38   264.5  658.04   274.3  661.04   284.1   662.8   372.3  666.83
   411.5  669.29   431.1  670.94   470.3  674.73   480.1  675.92   509.4  680.38
#Mann= 3 , 0 , 0
       0      .1       0   244.9    .045       0   274.3      .1       0
#XS Ineff= 2 , 0
          204.61  671.81
Permanent Ineff=
       F       F
Bank Sta=244.9,274.3
XS Rating Curve= 0 ,0
Exp/Cntr=0.3,0.1

Type RM Length L Ch R = 1 ,1887.4  ,113.4,111.8,110.5
XS GIS Cut Line= 2
     1745783.502      516875.622     1746185.846      517188.122
#Sta/Elev= 30
       0  690.86    39.2  675.36      49  673.95    68.6  672.58    78.4  672.55
      98  671.78   117.6   669.4   137.2   668.4   166.6  664.31   176.4   661.7
   186.1  661.42   195.9  664.04   205.7  665.97   215.5  666.19   225.3   665.4
   235.1  663.34   244.9  660.27   254.7  657.59   264.5  658.34   274.3   660.8
   284.1  661.96   293.9  662.09   313.5   661.6   342.9  662.66   401.7  666.61
   431.1  668.93   440.9  670.12   470.3  674.67   480.1  676.33   509.4  682.01
#Mann= 3 , 0 , 0
       0      .1       0   244.9    .045       0   274.3      .1       0
#XS Ineff= 2 , 0
          212.58  668.47
Permanent Ineff=
       F       F
Bank Sta=244.9,274.3
XS Rating Curve= 0 ,0
Exp/Cntr=0.3,0.1

Type RM Length L Ch R = 1 ,1775.6  ,167.9,165.3,162.4
XS GIS Cut Line= 2
      1745813.45      517052.706     1746170.221      517289.685
#Sta/Elev= 30
       0  684.47     9.7  682.78    19.5  679.16    29.2  675.11    48.7  670.54
    58.4  667.33    68.1  664.95    77.9  664.61    87.6  665.26    97.3  665.29
   107.1  664.75   116.8  663.33     128  660.15   136.3  657.72     146  657.53
   155.8  659.33   165.5  660.09   223.9  661.15   282.3  662.62   301.8  663.71
   311.5   664.5   321.2  665.68     331  667.58   340.7   670.2   350.4  673.33
   379.6  683.92   389.4  687.18   399.1  689.67   408.8  691.19   428.3  693.19
#Mann= 3 , 0 , 0
       0      .1       0     128    .045       0   155.8      .1       0
Bank Sta=128,155.8
XS Rating Curve= 0 ,0
Exp/Cntr=0.3,0.1

Type RM Length L Ch R = 1 ,1610.3  ,185.5,190.3,195
XS GIS Cut Line= 2
      1745713.19      517194.633     1746178.033      517434.216
#Sta/Elev= 30
       0  679.21     9.7  676.17    19.4  673.74      29  671.74    48.4  667.02
    58.1   665.5    77.5  663.78    87.2  663.22   106.5  664.21   116.2  664.22
   164.6  663.46   174.3  663.06     184  661.54   187.6  659.87   193.7  657.53
   203.4  656.87   211.9  659.92   222.7  662.47   261.5  664.23   271.2  664.49
   377.7  665.54   387.4  666.48   416.4     672   426.1  674.18   455.2  681.67
   464.8   683.8   474.5  685.52   493.9  687.85   513.3  689.01     523  689.16
#Mann= 3 , 0 , 0
       0     .06       0   187.6    .045       0   211.9     .08       0
Bank Sta=187.6,211.9
XS Rating Curve= 0 ,0
Exp/Cntr=0.3,0.1

Type RM Length L Ch R = 1 ,1420    ,99.6,100.1,100.7
XS GIS Cut Line= 4
     1745641.358      517345.385     1745685.846      517355.151
     1745887.669      517518.996     1745963.624      517662.225
#Sta/Elev= 30
       0  679.73    18.2  675.73    45.6  669.01    55.2  666.25    64.8  663.07
    74.4  661.39   112.9  662.89   161.1  662.56   199.6  661.66   209.2  659.25
   218.8  656.97   228.5  657.46  233.39  658.95   238.1  660.94   247.7   662.3
   276.6   663.8   286.2   664.6   295.9  665.87   305.5  667.45   324.6  674.08
   343.6  680.25   353.2   683.7   372.3  692.08   381.8  696.49   391.3  699.86
   400.9  701.66   410.4  702.41   419.9   702.8     439  702.88   467.6  703.56
#Mann= 3 , 0 , 0
       0     .06       0   209.2    .045       0  233.39     .08       0
Bank Sta=209.2,233.39
XS Rating Curve= 0 ,0
Exp/Cntr=0.3,0.1

Type RM Length L Ch R = 1 ,1319.9  ,69.5,68.2,67.1
XS GIS Cut Line= 3
      1745586.02       517430.02     1745644.613      517443.041
     1745888.754      517653.545
#Sta/Elev= 30
       0  680.95    17.2  677.76    34.3  673.77    42.9  671.59    51.4  669.16
      60  666.22    69.8  663.25    79.6  661.08    89.3  661.25   118.6  662.92
   128.4  663.09   147.9   663.1   177.2  662.74     187  662.47   196.8  661.62
   206.6  658.42   216.3  656.46   226.1  658.31   226.9  658.64   235.9  662.35
   245.6  665.57   274.9  674.91   284.7  678.22     314  688.95   323.8  691.91
   333.5  695.37   343.3  699.08   353.1   700.9   362.8  701.59   382.4  702.29
#Mann= 3 , 0 , 0
       0     .08       0   206.6    .045       0   226.9      .1       0
Bank Sta=206.6,226.9
XS Rating Curve= 0 ,0
Exp/Cntr=0.3,0.1

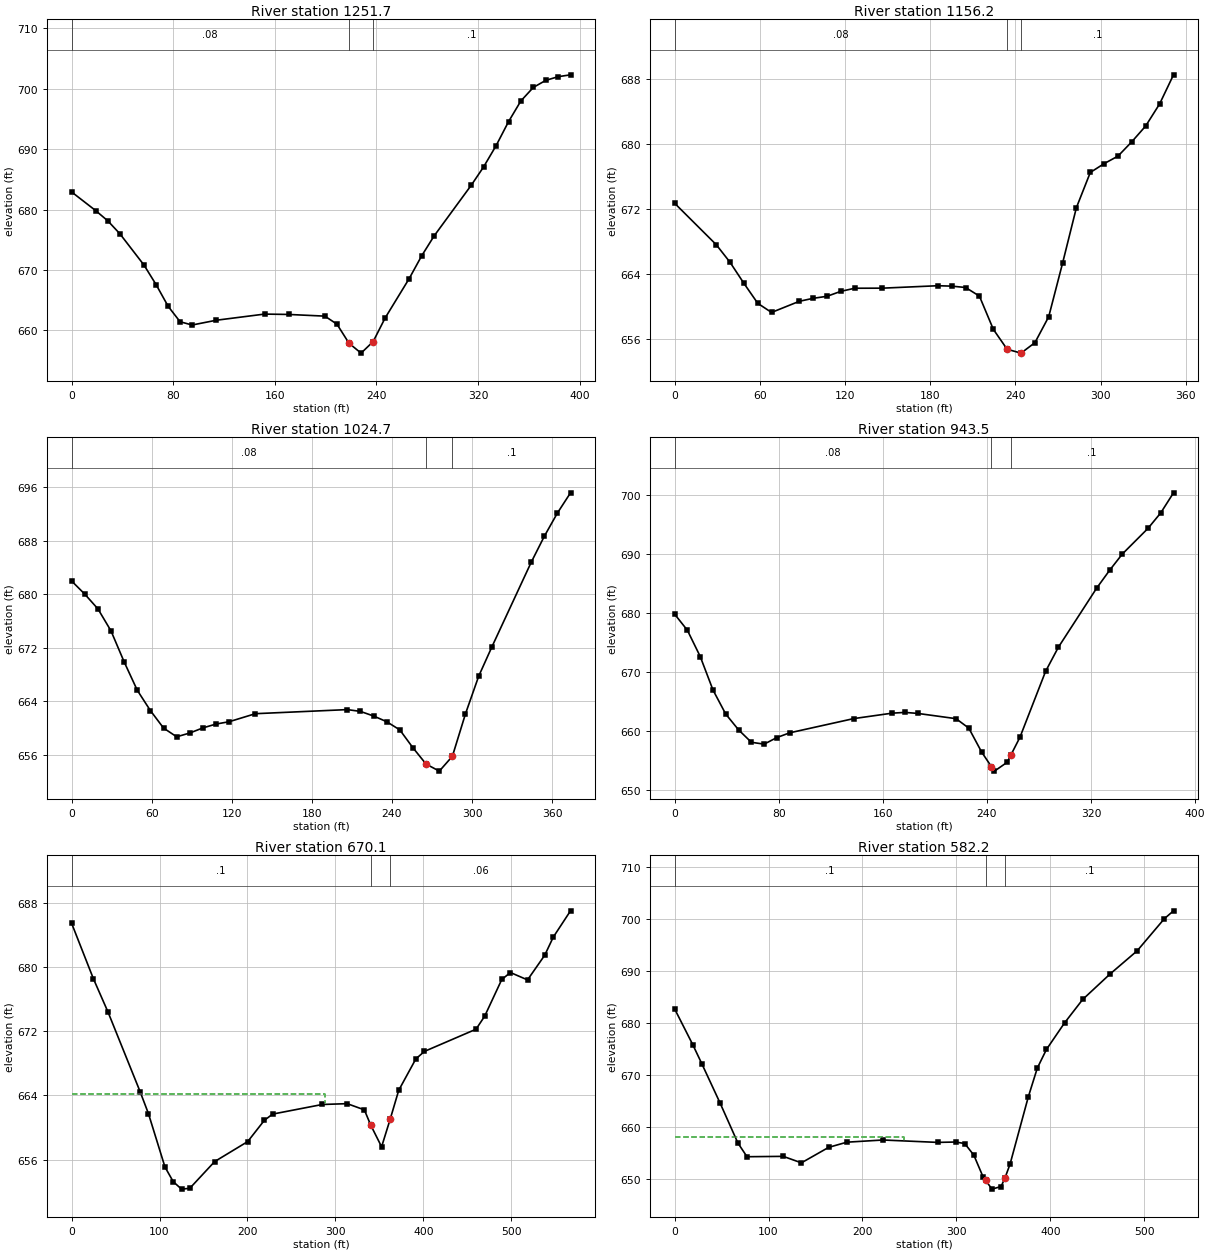
Type RM Length L Ch R = 1 ,1251.7  ,95.2,95.5,95.7
XS GIS Cut Line= 3
     1745546.957      517467.998     1745759.631      517627.503
     1745876.818      517676.331
#Sta/Elev= 30
       0  682.91      19  679.81    28.5  678.12      38  675.98      57  670.79
    66.5  667.56      76  663.96    85.4   661.4    94.9  660.86   113.9  661.65
   151.9  662.67   170.9  662.61   199.4  662.33   208.9     661   218.4  657.84
   227.9   656.2   237.4  658.11   246.8  662.01   265.8  668.56   275.6  672.32
   285.4  675.62   314.7  684.04   324.4  687.07   334.2  690.58     344  694.56
   353.7  697.99   363.5  700.23   373.3   701.4     383  702.01   392.8  702.32
#Mann= 3 , 0 , 0
       0     .08       0   218.4    .045       0   237.4      .1       0
Bank Sta=218.4,237.4
XS Rating Curve= 0 ,0
Exp/Cntr=0.3,0.1

Type RM Length L Ch R = 1 ,1156.2  ,128.2,131.6,134.7
XS GIS Cut Line= 2
      1745508.98      517547.208     1745787.842      517760.967
#Sta/Elev= 30
       0  672.66    29.3  667.56      39   665.4    48.8   662.8    58.6  660.33
    68.3  659.21    87.8  660.58    97.6  660.95   107.4   661.2   117.1  661.81
   126.9  662.19   146.4   662.2   185.4   662.5   195.2  662.45     205  662.28
   214.7  661.22   224.5  657.13   234.2  654.68     244   654.2   253.8  655.49
   263.5  658.68   273.3   665.3     283  672.11   292.8  676.45   302.6  677.54
   312.3  678.46   322.1  680.24   331.8  682.17   341.6  684.88   351.4  688.47
#Mann= 3 , 0 , 0
       0     .08       0   234.2    .045       0     244      .1       0
Bank Sta=234.2,244
XS Rating Curve= 0 ,0
Exp/Cntr=0.3,0.1

Type RM Length L Ch R = 1 ,1024.7  ,77.7,81.2,84.8
XS GIS Cut Line= 2
     1745449.301      517606.887     1745705.377      517879.239
#Sta/Elev= 30
       0  681.98     9.8  680.03    19.7  677.82    29.5  674.53    39.4  669.88
    49.2  665.66      59  662.63    68.9  660.01    78.7  658.71    88.5  659.27
    98.4  660.04   108.2  660.61     118  660.96   137.7  662.16   206.6  662.77
   216.4   662.5   226.3  661.81   236.1  660.96   245.9  659.74   255.8  657.05
   265.6  654.63   275.5  653.58   285.3   655.8   295.1  662.14     305  667.76
   314.8   672.1   344.3  684.76   354.2  688.67     364  692.14   373.8  695.15
#Mann= 3 , 0 , 0
       0     .08       0   265.6    .045       0   285.3      .1       0
Bank Sta=265.6,285.3
XS Rating Curve= 0 ,0
Exp/Cntr=0.3,0.1

Type RM Length L Ch R = 1 ,943.5   ,270.9,273.4,275.4
XS GIS Cut Line= 2
      1745431.94      517649.204     1745647.869      517966.045
#Sta/Elev= 30
       0  679.81     9.8  677.09    19.7  672.64    29.5  666.98    39.3  662.91
    49.2  660.23      59  658.14    68.8  657.82    78.6  658.94    88.5  659.74
   137.6  662.14   167.1  663.06     177  663.19   186.8  663.02   216.3  662.13
   226.1  660.53     236  656.47   243.5  654.01   245.8  653.26   255.6  654.76
   258.5  656.01   265.4  658.99   285.1  670.13   294.9   674.2   324.4  684.22
   334.3  687.22   344.1  689.98   363.8  694.31   373.6  696.93   383.4  700.32
#Mann= 3 , 0 , 0
       0     .08       0   243.5    .045       0   258.5      .1       0
Bank Sta=243.5,258.5
XS Rating Curve= 0 ,0
Exp/Cntr=0.3,0.1

Type RM Length L Ch R = 1 ,670.1   ,88,87.9,88
XS GIS Cut Line= 5
     1745176.558      517773.727     1745205.855      517813.875
     1745287.235      517951.678     1745364.492      518020.906
     1745487.105      518243.345
#Sta/Elev= 30
       0  685.44    24.8  678.53    41.4  674.39    77.9  664.48    87.4  661.74
   106.2  655.09   115.6  653.27     125  652.34   134.4  652.44   162.7  655.77
   200.3  658.26   219.2   660.9   228.6  661.68   285.2  662.88   313.5  662.98
     333  662.21   340.1  660.34   352.6  657.61   362.3  661.02   372.1  664.65
   391.6  668.56   401.4  669.49     460  672.25   469.8  673.86   489.3  678.44
   499.1  679.31   518.6  678.39   538.2  681.47   547.9  683.72   567.5  686.99
#Mann= 3 , 0 , 0
       0      .1       0   340.1    .045       0   362.3     .06       0
#XS Ineff= 2 , 0
          288.57  664.13
Permanent Ineff=
       F       F
Bank Sta=340.1,362.3
XS Rating Curve= 0 ,0
Exp/Cntr=0.3,0.1

Type RM Length L Ch R = 1 ,582.2   ,39.1,38,36.9
XS GIS Cut Line= 3
     1745143.311      517808.623     1745180.204      517865.046
     1745402.643      518271.947
#Sta/Elev= 30
       0  682.72    19.3  675.84    28.9  672.18    48.2  664.67    67.4  656.88
    77.1  654.24   115.7  654.31     135  653.06     164  656.04   183.4  657.04
     222  657.46     280     657   299.3  657.07   308.9  656.78   318.6  654.55
   328.3  650.42   331.2  649.69   337.9     648   347.6   648.5  351.82  650.18
   357.2  652.83   376.6  665.76   386.2  671.31   395.9  674.89   415.2  680.01
   434.5  684.52   463.5   689.4   492.5  693.89   521.5  700.08   531.2  701.59
#Mann= 3 , 0 , 0
       0      .1       0   331.2    .045       0  351.82      .1       0
#XS Ineff= 2 , 0
          244.46  658.04
Permanent Ineff=
       F       F
Bank Sta=331.2,351.82
XS Rating Curve= 0 ,0
Exp/Cntr=0.3,0.1

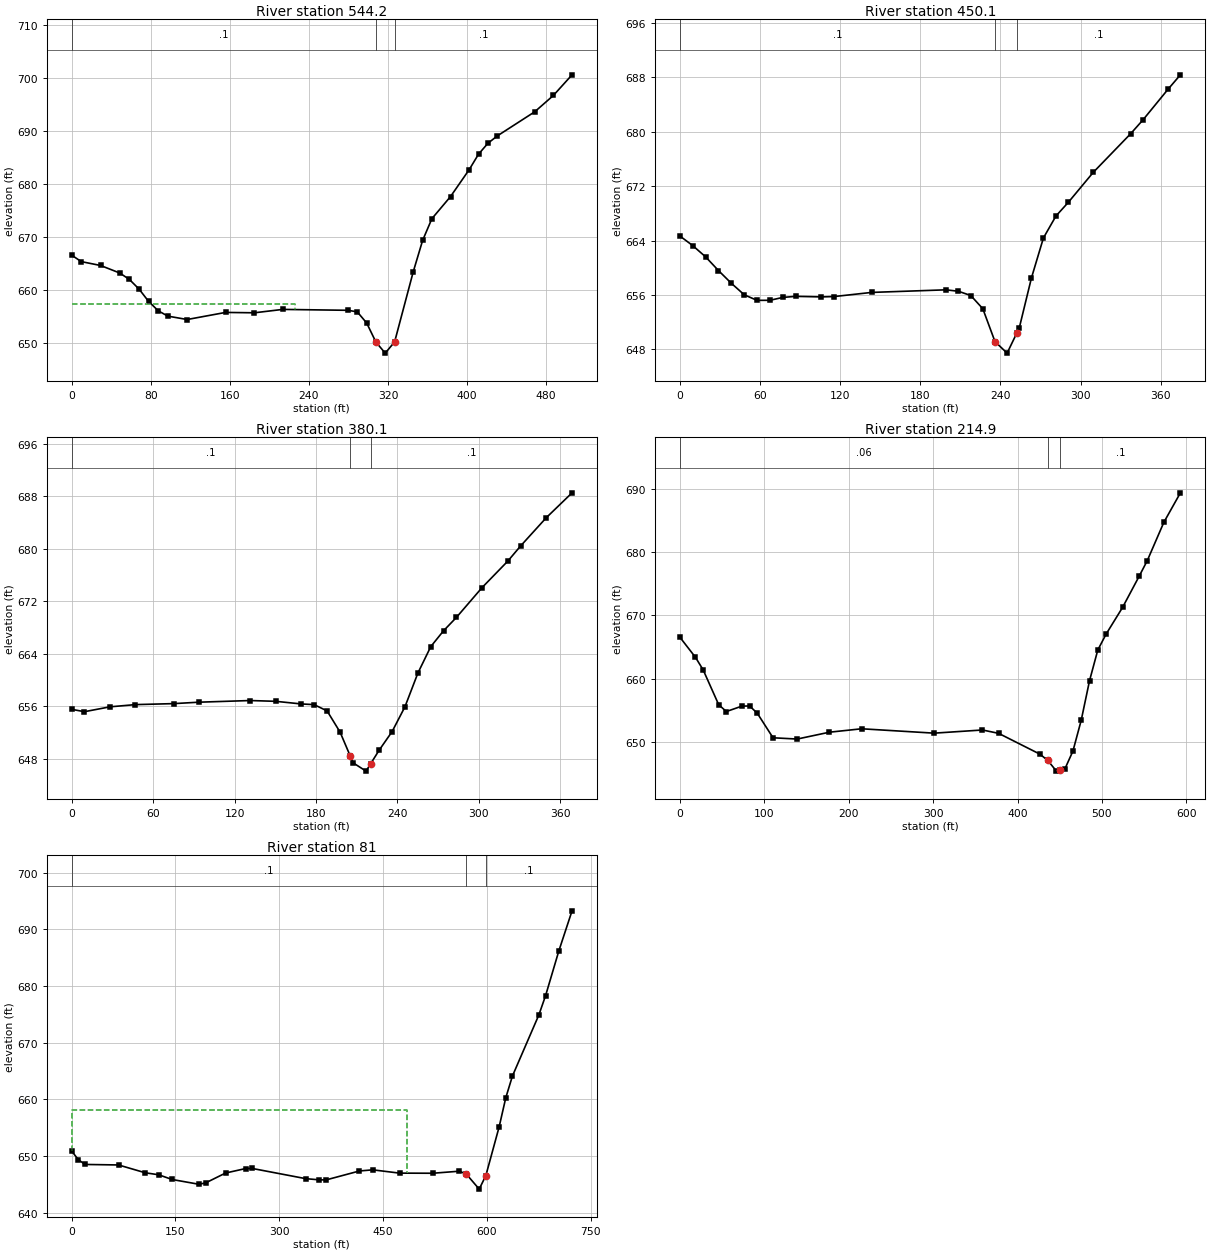
Type RM Length L Ch R = 1 ,544.2   ,99.8,94.1,88.4
XS GIS Cut Line= 4
     1745041.488      517927.894     1745214.014      518017.954
      1745307.33      518170.949     1745399.407      518266.029
#Sta/Elev= 30
       0  666.61     9.7  665.39    29.2  664.66    48.6  663.24    58.4  662.02
    68.1  660.21    77.8  657.88    87.6  656.09    97.3  655.09   116.8  654.45
   155.7  655.79   184.9  655.72   213.5  656.36   279.5  656.19   288.9   655.9
   298.4   653.8   307.8  650.18   317.2   648.1   326.7  650.22   345.5  663.44
     355  669.38   364.4   673.5   383.3  677.69   402.2  682.78   411.6  685.69
   421.1  687.75   430.6  689.14   468.4  693.69   487.3  696.78   506.2  700.68
#Mann= 3 , 0 , 0
       0      .1       0   307.8    .045       0   326.7      .1       0
#XS Ineff= 2 , 0
          225.86  657.41
Permanent Ineff=
       F       F
Bank Sta=307.8,326.7
XS Rating Curve= 0 ,0
Exp/Cntr=0.3,0.1

Type RM Length L Ch R = 1 ,450.1   ,74.8,69.9,64.6
XS GIS Cut Line= 5
     1745034.414      517998.857     1745135.325      518072.642
     1745179.813      518154.022     1745218.875         518192.
     1745313.277      518232.147
#Sta/Elev= 30
       0  664.65     9.6  663.24    19.2  661.59    28.8  659.58    38.5   657.7
    48.1  656.02    57.7   655.2    67.3  655.21    76.9  655.63    86.5  655.79
   105.8  655.71   115.4  655.76   143.6  656.37   199.2  656.75   208.5  656.54
   217.8  655.91   226.8  653.97   235.9  649.14     245  647.44   252.1  650.33
   254.1  651.14   263.2  658.48   272.2  664.38   281.6  667.61   290.9  669.63
   309.5  674.02   337.5   679.7   346.8  681.75   365.5  686.24   374.8  688.37
#Mann= 3 , 0 , 0
       0      .1       0   235.9    .045       0   252.1      .1       0
Bank Sta=235.9,252.1
XS Rating Curve= 0 ,0
Exp/Cntr=0.3,0.1

Type RM Length L Ch R = 1 ,380.1   ,178.4,165.3,152.2
XS GIS Cut Line= 4
     1745023.954      518060.446     1745124.648      518208.015
      1745181.94      518242.737     1745303.467      518261.835
#Sta/Elev= 28
       0  655.56     9.4   655.2    28.2  655.94      47  656.28    75.2  656.43
      94  656.65   131.6   656.9   150.4  656.78   169.2  656.38   178.6  656.28
   188.2  655.32   197.8  652.08   205.2  648.48   207.4  647.41   216.9  646.15
   220.2  647.24   226.5  649.32   236.1  652.17   245.6  655.96   255.1  661.08
   264.6  665.11     274  667.52   283.5  669.56   302.4   674.1   321.4  678.14
   330.8  680.44   349.7  684.74   368.7  688.53
#Mann= 3 , 0 , 0
       0      .1       0   205.2    .045       0   220.2      .1       0
Bank Sta=205.2,220.2
XS Rating Curve= 0 ,0
Exp/Cntr=0.3,0.1

Type RM Length L Ch R = 1 ,214.9   ,132.8,133.8,134.9
XS GIS Cut Line= 4
      1744775.69      518131.626      1744846.87      518202.807
     1745055.204      518385.099     1745270.481      518378.154
#Sta/Elev= 30
       0  666.51    18.3  663.37    27.4  661.39    45.8   655.9    54.9  654.82
    73.2  655.67    82.4   655.7    91.5  654.56   110.2  650.68   138.8  650.48
     177  651.56   215.2   652.1   301.1  651.41   358.4  651.91   377.5  651.38
   426.4   648.1   435.8   647.1     446  645.42   450.8  645.56   455.8   645.7
   465.6   648.6   475.4  653.46   485.2  659.67     495  664.52   504.8  667.02
   524.4  671.25   543.9  676.13   553.7  678.64   573.3  684.67   592.9  689.32
#Mann= 3 , 0 , 0
       0     .06       0   435.8    .045       0   450.8      .1       0
Bank Sta=435.8,450.8
XS Rating Curve= 0 ,0
Exp/Cntr=0.3,0.1

Type RM Length L Ch R = 1 ,81      ,75.8,81,86.2
XS GIS Cut Line= 3
     1744591.662      518298.293     1745023.954      518515.307
     1745263.537      518518.779
#Sta/Elev= 30
       0  650.92     9.7  649.37    19.4  648.55    67.7  648.46   106.4  647.08
   125.8  646.73   145.1   645.9   183.8  645.06   193.5  645.29   222.5  647.04
   251.5  647.83   261.2  647.84   338.6  646.04   357.9  645.84   367.6  645.82
     416   647.4   435.3   647.6     474  647.02     522     647   560.4  647.36
   570.4  646.86   589.1   644.2   598.7  646.59   617.9  655.17   627.5   660.3
   637.1  664.13   675.4  674.93     685  678.29   704.2  686.19   723.3  693.26
#Mann= 3 , 0 , 0
       0      .1       0   570.4    .045       0   598.7      .1       0
#XS Ineff= 2 , 0
          485.39  658.14
Permanent Ineff=
       F       F
Bank Sta=570.4,598.7
XS Rating Curve= 0 ,0
Exp/Cntr=0.3,0.1

Chan Stop Cuts=-1
Use User Specified Reach Order=0
Composite Channel Slope=5